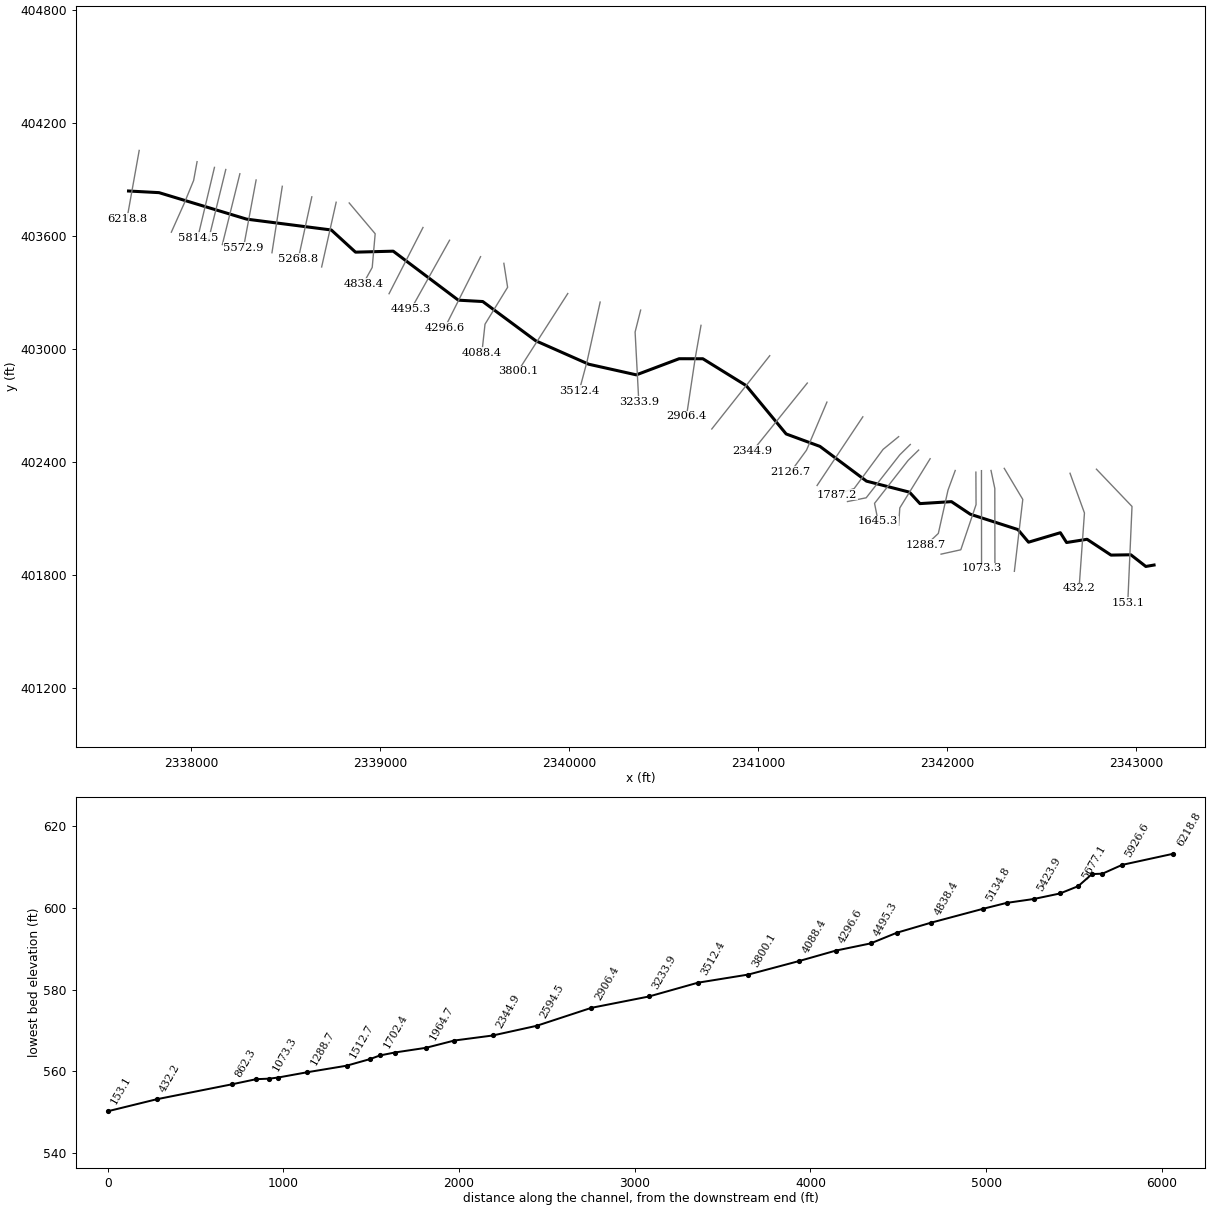
--- YLLWSPRGRN.prj (project) ---

Proj Title=YLLWSPRGRN
Current Plan=p01
Default Exp/Contr=0,0
English Units
Geom File=g01
Flow File=f01
Plan File=p01
BEGIN DESCRIPTION:
END DESCRIPTION:
DSS Export Rating Curves= 0
DSS Export Rating Curve Sorted= 0
DSS Export Volume Flow Curves= 0
DXF OffsetX= 0
DXF OffsetY= 0
DXF ScaleX= 0
DXF ScaleY= 0

--- YLLWSPRGRN.p01 (plan) ---

Plan Title=Floodplain
Program Version=4.00
Geom File=g01
Flow File=f01
K Sum by GR=0
Std Step Tol=0.01
Critical Tol=0.01
Num of Std Step Trials=20
Max Error Tol=0.3
Flow Tol Ratio=0.001
Split Flow NTrial=30
Split Flow Tol=0.02
Split Flow Ratio=0.02
Log Output Level=0
Friction Slope Method=1
Unsteady Friction Slope Method=2
Unsteady Bridges Friction Slope Method=1
Global Log Level=0
CheckData=False
Run HTab=0
Run UNet=0
Run PostProcess=0
UNET Theta=0
UNET Theta Warmup=0
UNET ZTol=0
UNET ZSATol=0
UNET MxIter=0
UNET MaxInSteps=0
UNET DtIC=0
UNET DtMin=0
UNET MaxCRTS=0
UNET WFStab=0
UNET SFStab=0
UNET WFX=0
UNET SFX=0
UNET DSS MLevel=0
UNET DZMax Abort=0
UNET Convert EG Bridges=0
UNET Use Existing IB Tables=0
UNET Froude Limit=0
UNET Froude Power=0
Write IC File=0
Echo Input=False
Echo Output=False
Write Detailed=0

--- YLLWSPRGRN.f01 (steady flow) ---

Flow Title=NFF Regression Equation
Program Version=4.00
Number of Profiles=1
Profile Names=P100yr
River Rch & RM=YLLWSPRGRN,Main      ,6218.8
548.5824
River Rch & RM=YLLWSPRGRN,Main      ,4644.7
561.1013
River Rch & RM=YLLWSPRGRN,Main      ,4495.3
669.4886
River Rch & RM=YLLWSPRGRN,Main      ,4088.4
692.0277
River Rch & RM=YLLWSPRGRN,Main      ,2594.5
760.2949
River Rch & RM=YLLWSPRGRN,Main      ,432.2
840.9670
River Rch & RM=YLLWSPRGRN,Main      ,153.1
845.5680
Boundary for River Rch & Prof#=YLLWSPRGRN,Main      ,1
Up Type=0
Dn Type=3
Dn Slope=0.009423

--- YLLWSPRGRN.g01 (geometry) ---

Geom Title=USGS 10m DEM
Program Version=4.10

River Reach=YLLWSPRGRN      ,Main
Reach XY= 30
     2337668.169      403836.718     2337829.627      403828.037
     2338293.169      403687.412     2338741.463      403629.783
     2338869.558      403512.065     2339069.211      403517.274
     2339413.857      403257.156     2339543.169      403249.913
     2339823.905      403041.336     2340104.178      402917.009
     2340356.001      402860.585     2340582.564      402946.262
       2340708.1      402946.093     2340937.266      402803.732
     2341149.072      402546.787     2341327.891      402480.815
     2341574.361      402296.298      2341801.85       402237.76
     2341857.405      402176.996     2342024.072      402187.412
      2342123.84      402120.604     2342375.663      402039.267
     2342432.058      401972.135     2342600.461      402022.482
     2342633.447      401970.398     2342741.809      401987.618
     2342868.588      401903.633     2342973.666      401905.261
     2343052.833      401843.282     2343096.496       401850.86

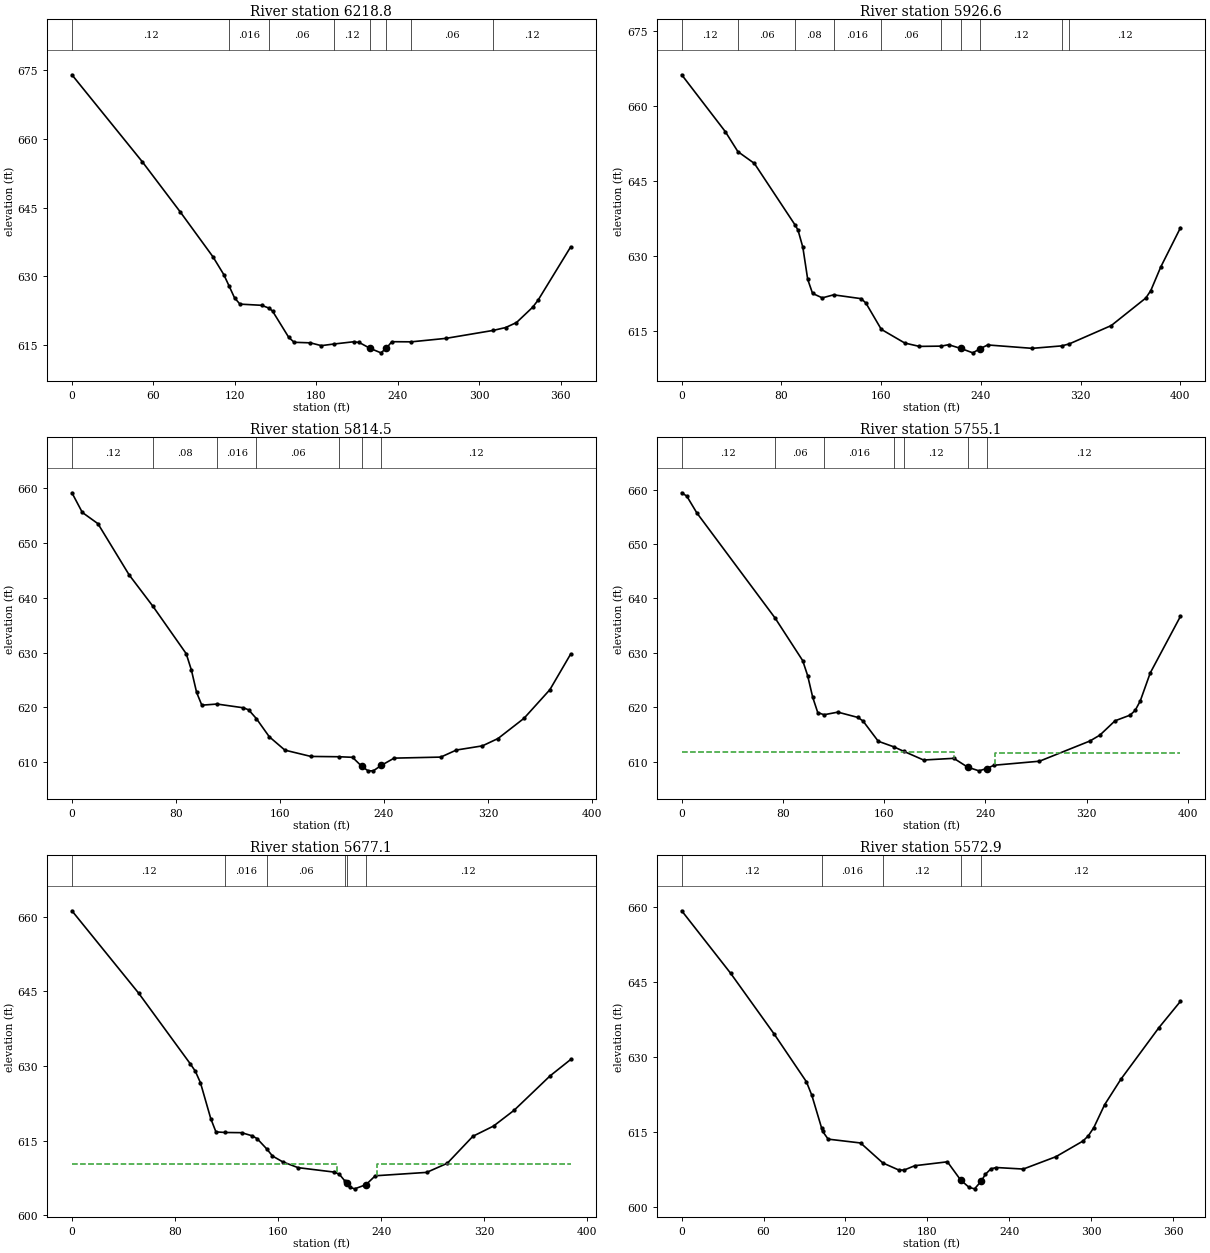
Type RM Length L Ch R = 1 ,6218.8  ,297,292.2,286.6
XS GIS Cut Line= 2
     2337724.599      404052.151     2337660.162      403690.679
#Sta/Elev= 30
       0  673.97    51.9  654.96    79.8  644.03   103.8  634.27   111.8  630.38
  115.71627.8835   119.7  625.31   123.7  623.93   139.7  623.67   145.1623.0535
   147.7  622.41   159.6  616.69   163.6   615.6   175.6  615.48   183.6  614.87
  192.79615.2219   207.5  615.72   211.5  615.56   219.5  614.28   227.5   613.3
   231.5  614.31   235.5  615.73  249.88 615.702   275.4  616.46  310.24618.1985
   319.3  618.82   327.3  619.91   339.2  623.25   343.2   624.8   367.2  636.42
#Mann= 8 ,-1 , 0
       0     .12       0  115.71    .016       0   145.1     .06       0
  192.79     .12       0   219.5    .045       0   231.5     .12       0
  249.88     .06       0  310.24     .12       0
Bank Sta=219.5,231.5
XS Rating Curve= 0 ,0
Exp/Cntr=0.3,0.1

Type RM Length L Ch R = 1 ,5926.6  ,108.6,112.1,116.3
XS GIS Cut Line= 4
     2338030.951      403992.438     2338012.823         403893.
     2337962.623      403770.355     2337894.761      403618.185
#Sta/Elev= 30
       0  666.25      35  654.86    45.1650.8532    58.3   648.5   90.81636.2262
    93.3  635.16    97.2   631.7   101.1  625.28     105  622.46   112.8  621.57
  121.89622.1765     144  621.41   147.8  620.53  160.13615.2678     179  612.52
   190.7  611.85  208.42611.9053   214.1  612.19  224.02611.4326   233.6  610.56
  239.14 611.354   245.5  612.14   281.2  611.46  304.86611.9527  310.92612.3425
   344.7  616.03   372.4  621.54   376.4  623.04   384.4  627.77   400.2  635.62
#Mann= 10 ,-1 , 0
       0     .12       0    45.1     .06       0   90.81     .08       0
  121.89    .016       0  160.13     .06       0  208.42     .12       0
  224.02    .045       0  239.14     .12       0  304.86     .06       0
  310.92     .12       0
Bank Sta=224.02,239.14
XS Rating Curve= 0 ,0
Exp/Cntr=0.3,0.1

Type RM Length L Ch R = 1 ,5814.5  ,59.6,59.4,59.3
XS GIS Cut Line= 2
     2338123.008      403962.213     2338034.466      403588.949
#Sta/Elev= 30
       0  659.17       8  655.58      20  653.53      44  644.18   62.37638.4232
    87.9  629.79    91.9  626.79    95.9  622.72    99.9  620.39  111.59620.5952
   131.9  619.91   135.9  619.54  141.88617.9324   151.8  614.62   163.8  612.18
   183.8  611.03  205.51 610.973   215.8  610.87   222.8  609.25   227.8   608.4
   231.8   608.4   237.8  609.38   247.8  610.72   283.7  610.91   295.7   612.2
   315.7  612.96   327.7   614.3   347.7  617.99   367.6  623.22   383.6  629.73
#Mann= 7 ,-1 , 0
       0     .12       0   62.37     .08       0  111.59    .016       0
  141.88     .06       0  205.51     .12       0   222.8    .045       0
   237.8     .12       0
Bank Sta=222.8,237.8
XS Rating Curve= 0 ,0
Exp/Cntr=0.3,0.1

Type RM Length L Ch R = 1 ,5755.1  ,77.9,78,77.8
XS GIS Cut Line= 2
     2338182.904      403950.928     2338089.154      403568.115
#Sta/Elev= 30
       0  659.42       4  658.81    11.9  655.74   73.81636.3875    95.6  628.57
    99.5  625.82   103.5  621.84   107.5  619.02  112.46618.6214   123.4   619.1
   139.3  618.12   143.3  617.46   155.3  613.75  167.47612.7322  175.39611.9038
   191.1   610.3     215  610.61     226  608.98   234.9  608.31     241  608.74
   246.8  609.34   282.7  610.08   322.5  613.79   330.4  614.87   342.4  617.51
   354.3  618.55   358.3  619.42   362.3  621.14   370.2   626.3   394.1  636.72
#Mann= 7 ,-1 , 0
       0     .12       0   73.81     .06       0  112.46    .016       0
  167.47     .06       0  175.39     .12       0     226    .045       0
     241     .12       0
#XS Ineff= 2 , 0
          215.48  611.76  247.68          611.55
Permanent Ineff=
       F       F
Bank Sta=226,241
XS Rating Curve= 0 ,0
Exp/Cntr=0.3,0.1

Type RM Length L Ch R = 1 ,5677.1  ,102.9,104.2,105.5
XS GIS Cut Line= 2
     2338257.557      403928.359     2338164.675       403552.49
#Sta/Elev= 30
       0  661.15    51.9  644.59    91.8  630.47    95.8  628.96    99.8  626.63
   107.8  619.43   111.8  616.78  119.04 616.658   131.7  616.62   139.7  616.01
   143.7  615.44  151.21613.3707   155.7  611.94   163.6  610.77   175.6   609.6
   203.6  608.71   207.6  608.28  211.77606.9711   213.3  606.44   215.5  605.68
   219.5  605.35   228.3  606.19   235.5  607.97   275.4  608.65   291.4  610.48
   311.3   615.9   327.3  617.95   343.3  621.12   371.2  628.02   387.2  631.31
#Mann= 6 ,-1 , 0
       0     .12       0  119.04    .016       0  151.21     .06       0
  211.77     .12       0   213.3    .045       0   228.3     .12       0
#XS Ineff= 2 , 0
          205.99  610.29  236.95          610.29
Permanent Ineff=
       F       F
Bank Sta=213.3,228.3
XS Rating Curve= 0 ,0
Exp/Cntr=0.3,0.1

Type RM Length L Ch R = 1 ,5572.9  ,148.3,149,149.7
XS GIS Cut Line= 2
     2338343.494      403895.372     2338276.654      403535.997
#Sta/Elev= 30
       0  659.21    35.8  646.72    67.6   634.6    91.4  624.98    95.4  622.24
  102.51615.7353   103.3  615.05   107.3   613.5   131.1  612.73   147.4 608.728
   158.9  607.34   162.9   607.3   170.8  608.18   194.7  608.96   204.4  605.32
   210.6  603.84   214.6  603.55   219.4  605.05   222.5  606.45   226.5  607.53
   230.4  607.82   250.3  607.51   274.2  609.98     294  613.11     298  614.17
     302  615.81   309.9  620.38   321.8  625.48   349.6  635.78   365.5  641.09
#Mann= 5 ,-1 , 0
       0     .12       0  102.51    .016       0   147.4     .12       0
   204.4    .045       0   219.4     .12       0
Bank Sta=204.4,219.4
XS Rating Curve= 0 ,0
Exp/Cntr=0.3,0.1

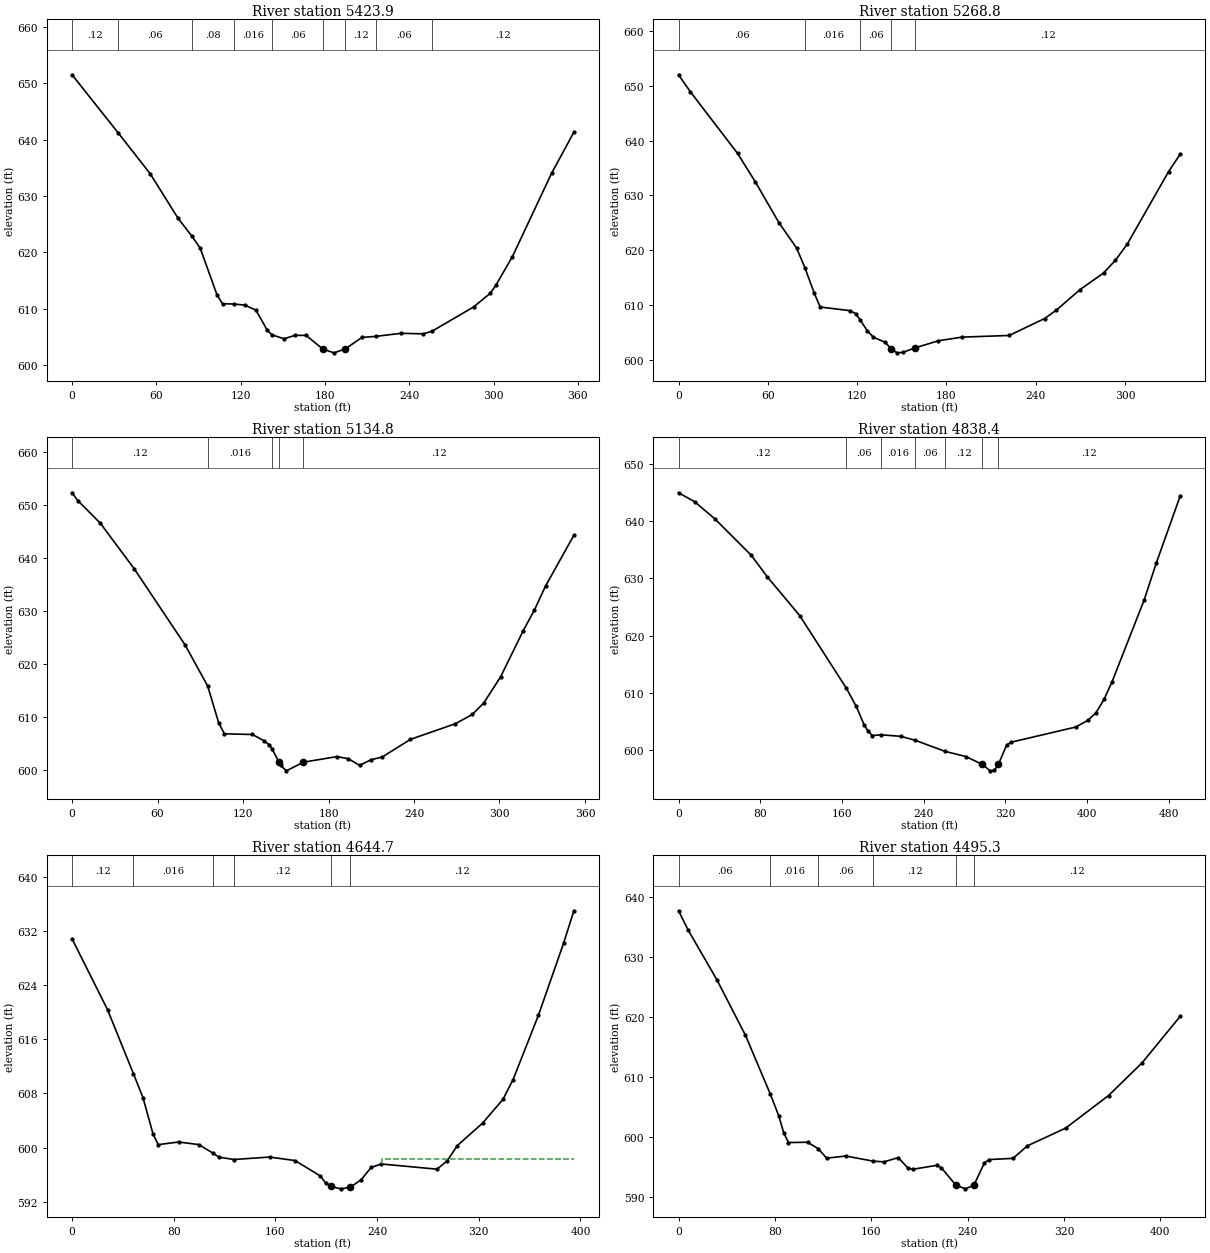
Type RM Length L Ch R = 1 ,5423.9  ,156.4,155.1,153.7
XS GIS Cut Line= 2
     2338482.057      403861.779      2338427.37      403508.914
#Sta/Elev= 30
       0  651.48   32.73641.2126    55.6  633.94    75.4  626.06   85.36 622.848
    91.2  620.75   103.2  612.43   107.1   610.9  115.15610.8505     123  610.65
   130.9  609.75   138.9   606.2  142.24 605.395   150.8  604.69   158.7   605.3
   166.6  605.29   178.5  602.85   186.5   602.2   194.4   602.9   206.3  604.93
  216.33605.1219   234.1  605.66     250  605.57  256.16606.0242   285.7  610.33
   297.6  612.75   301.5  614.14   313.4  619.27   341.2     634   357.1   641.3
#Mann= 9 ,-1 , 0
       0     .12       0   32.73     .06       0   85.36     .08       0
  115.15    .016       0  142.24     .06       0   178.5    .045       0
   194.4     .12       0  216.33     .06       0  256.16     .12       0
Bank Sta=178.5,194.4
XS Rating Curve= 0 ,0
Exp/Cntr=0.3,0.1

Type RM Length L Ch R = 1 ,5268.8  ,133.8,134,133.5
XS GIS Cut Line= 2
     2338638.307      403805.789     2338566.693      403476.362
#Sta/Elev= 30
       0     652     7.9  648.92    39.7  637.63    51.6  632.45    67.4  625.02
    79.3  620.38   84.85616.8137    91.2  612.11    95.2   609.6     115  608.95
     119   608.4   122.1607.2298   126.9  605.23   130.9  604.09   138.8  603.17
   142.8  601.97   146.8  601.24   150.7  601.32   158.6  602.12   174.5  603.44
   190.4  604.11   222.1  604.41   245.9   607.5   253.8  609.03   269.7  612.78
   285.6  615.83   293.5  618.14   301.4  621.07   329.2  634.32   337.1  637.54
#Mann= 5 ,-1 , 0
       0     .06       0   84.85    .016       0   122.1     .06       0
   142.8    .045       0   158.6     .12       0
Bank Sta=142.8,158.6
XS Rating Curve= 0 ,0
Exp/Cntr=0.3,0.1

Type RM Length L Ch R = 1 ,5134.8  ,293,296.5,299.8
XS GIS Cut Line= 2
     2338767.214      403777.143     2338690.391      403433.393
#Sta/Elev= 30
       0  652.28       4  650.82    19.8  646.55    43.5  637.98    79.2  623.61
    95.2615.7933   102.9  608.86   106.9  606.78   126.6  606.65   134.6  605.48
   138.5  604.69   140.4 603.892  145.33601.4063   146.4   600.8   150.4  599.79
   162.3  601.42     186  602.48   193.9  602.08   201.8  600.82   209.8  601.88
   217.7   602.4   237.5  605.73   269.1  608.69     281  610.45   288.9  612.58
   300.8  617.54   316.6  626.21   324.5  630.14   332.4  634.71   352.2  644.26
#Mann= 5 ,-1 , 0
       0     .12       0    95.2    .016       0   140.4     .12       0
  145.33    .045       0   162.3     .12       0
Bank Sta=145.33,162.3
XS Rating Curve= 0 ,0
Exp/Cntr=0.3,0.1

Type RM Length L Ch R = 1 ,4838.4  ,202.5,193.7,184.6
XS GIS Cut Line= 4
     2338836.224      403773.237     2338973.702      403609.782
     2338958.077      403430.963     2338910.443      403344.852
#Sta/Elev= 30
       0  644.94    15.8  643.38    35.6  640.38    71.2  634.03      87  630.25
   118.7  623.49  164.46610.7883     174  607.66   181.9  604.36   185.9   603.3
   189.8  602.54  198.19 602.675   217.6  602.41  231.53601.7345  261.12599.7772
   281.4  598.88   297.4  597.52   305.3  596.38   309.3  596.46   313.3  597.51
   321.3  600.85   325.3  601.36   389.1  604.03     401  605.21   408.8  606.51
   416.7  608.84   424.6  611.92   456.1  626.23   467.9  632.64   491.5  644.44
#Mann= 7 ,-1 , 0
       0     .12       0  164.46     .06       0  198.19    .016       0
  231.53     .06       0  261.12     .12       0   297.4    .045       0
   313.3     .12       0
Bank Sta=297.4,313.3
XS Rating Curve= 0 ,0
Exp/Cntr=0.3,0.1

Type RM Length L Ch R = 1 ,4644.7  ,150,149.4,148.3
XS GIS Cut Line= 2
     2339226.849      403643.029     2339047.162      403291.466
#Sta/Elev= 30
       0  630.82    27.9  620.37   48.29 610.921    55.8  607.38    63.8  601.97
    67.8  600.45    83.8  600.84    99.7  600.46  110.56599.2325   115.6   598.6
  127.41598.2586   155.5  598.62   175.5   598.1   195.4  595.82   199.4  594.81
   203.8  594.28   211.4  593.93   218.8  594.16   227.3  595.24   235.3  597.09
   243.3   597.6   287.1  596.83   295.1  598.06   303.1  600.31     323  603.63
     339  607.13     347  610.06   366.9  619.53   386.8  630.21   394.8  634.96
#Mann= 6 ,-1 , 0
       0     .12       0   48.29    .016       0  110.56     .06       0
  127.41     .12       0   203.8    .045       0   218.8     .12       0
#XS Ineff= 2 , 0
                          243.96          598.28
Permanent Ineff=
       F       F
Bank Sta=203.8,218.8
XS Rating Curve= 0 ,0
Exp/Cntr=0.3,0.1

Type RM Length L Ch R = 1 ,4495.3  ,197.4,198.7,199.4
XS GIS Cut Line= 2
     2339367.474       403575.32     2339164.675      403211.345
#Sta/Elev= 30
       0  637.74     7.9  634.55    31.8  626.24    55.6  616.94   76.25607.1175
    83.3  603.46    87.3  600.69    91.3  599.04   107.1  599.09  115.95598.0311
     123  596.43   138.9  596.79  161.88595.9267   170.6  595.82   182.5  596.52
   190.5  594.78   194.4  594.57   214.3  595.23   218.2  594.85   230.2  591.95
   238.1  591.31   245.2  591.89     254  595.64   257.9   596.2   277.8   596.4
   289.7  598.49   321.4  601.44   357.1  606.89   384.9  612.34   416.7  620.14
#Mann= 6 ,-1 , 0
       0     .06       0   76.25    .016       0  115.95     .06       0
  161.88     .12       0   230.2    .045       0   245.2     .12       0
Bank Sta=230.2,245.2
XS Rating Curve= 0 ,0
Exp/Cntr=0.3,0.1

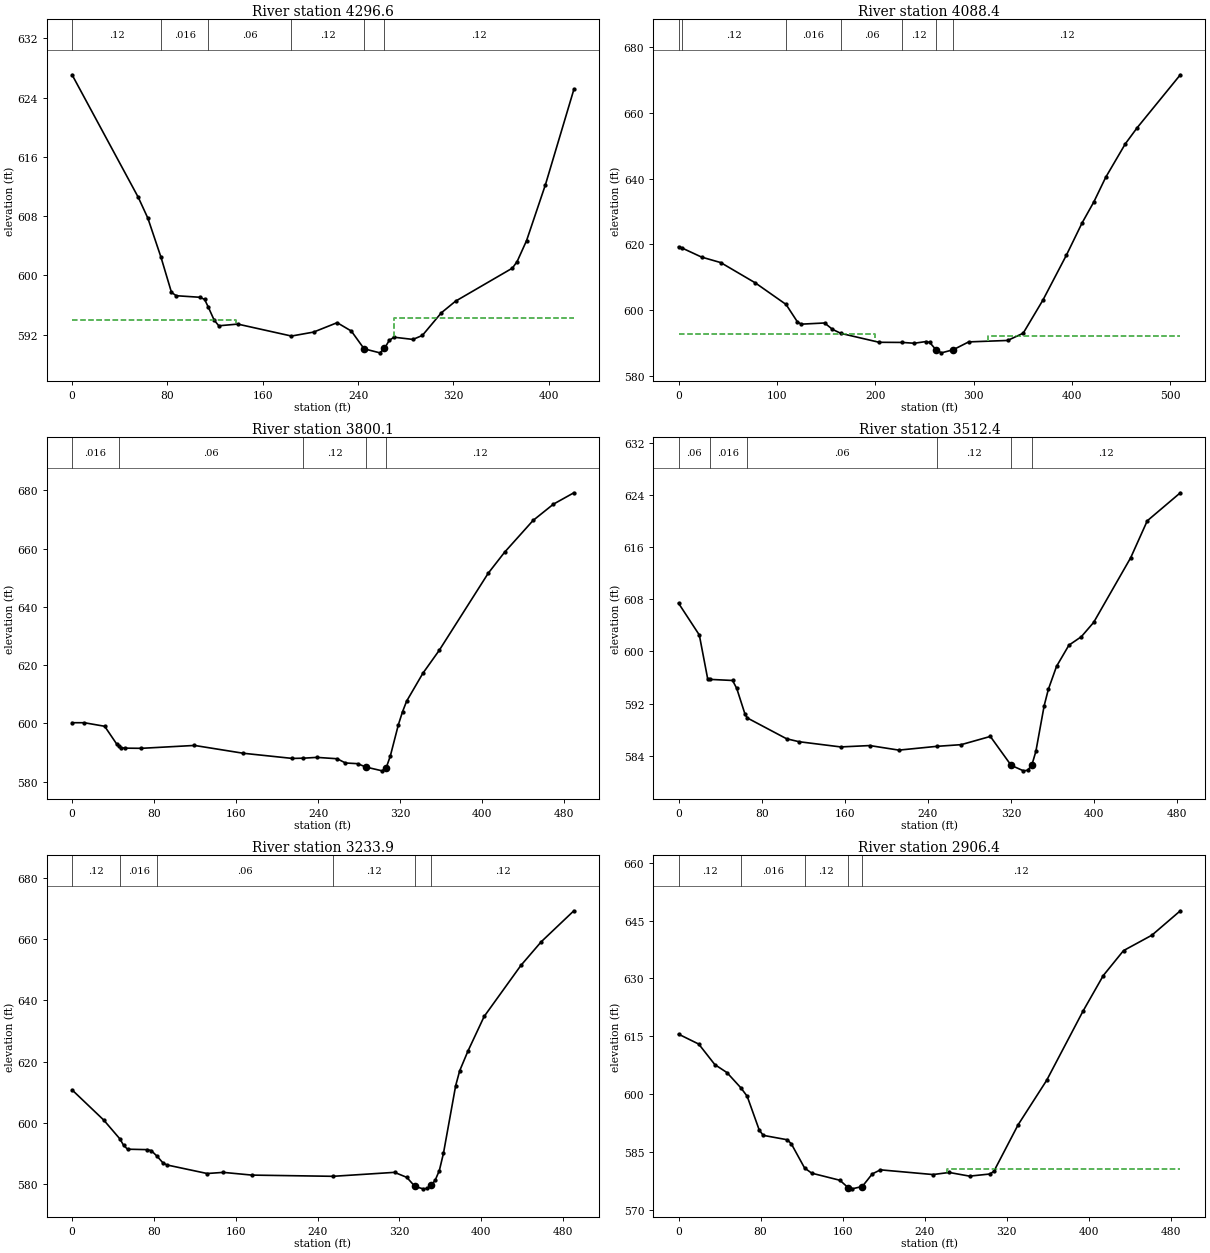
Type RM Length L Ch R = 1 ,4296.6  ,208.9,208.2,205.9
XS GIS Cut Line= 2
     2339531.537      403488.081     2339342.735      403111.779
#Sta/Elev= 30
       0  627.07    55.6  610.51    63.6  607.71   74.62602.4354    83.4   597.7
    87.4  597.25   107.2  597.04   111.2  596.75  114.32595.7048   119.2  593.96
   123.1  593.19     139  593.42  184.06591.8062   202.6  592.34   222.4  593.61
   234.3  592.48  245.02590.0843   258.2  589.54   262.1  590.13   266.1  591.22
   270.1  591.65     286  591.35   293.9  591.89   309.8  594.94   321.7  596.51
   369.4  600.97   373.4  601.86   381.3  604.68   397.2  612.26     421  625.09
#Mann= 6 ,-1 , 0
       0     .12       0   74.62    .016       0  114.32     .06       0
  184.06     .12       0  245.02    .045       0   262.1     .12       0
#XS Ineff= 2 , 0
          137.77  594.02  269.87          594.19
Permanent Ineff=
       F       F
Bank Sta=245.02,262.1
XS Rating Curve= 0 ,0
Exp/Cntr=0.3,0.1

Type RM Length L Ch R = 1 ,4088.4  ,288.5,288.4,287.5
XS GIS Cut Line= 4
     2339654.909      403452.707     2339674.718      403325.537
     2339555.104      403129.632      2339538.59      402978.749
#Sta/Elev= 30
       0  619.27    3.12 618.958    23.4  616.14    42.9  614.46      78  608.29
  109.28601.7198   120.9  596.38   124.8  595.72   148.5  596.08   156.4  594.15
  165.07592.9068   203.9   590.2   227.5590.1564   239.5  589.91   251.4  590.42
   255.3  590.15  261.73587.8974   267.2  586.99   279.1  587.92   294.9  590.32
   334.5  590.76   350.3  592.97   370.2  602.97   394.2  616.72   410.2  626.56
   422.2  632.99   434.1  640.38   454.1  650.62   466.1   655.5     510  671.63
#Mann= 7 ,-1 , 0
       0     .08       0    3.12     .12       0  109.28    .016       0
  165.07     .06       0   227.5     .12       0  261.73    .045       0
   279.1     .12       0
#XS Ineff= 2 , 0
             200  592.84  314.55          591.99
Permanent Ineff=
       F       F
Bank Sta=261.73,279.1
XS Rating Curve= 0 ,0
Exp/Cntr=0.3,0.1

Type RM Length L Ch R = 1 ,3800.1  ,279.7,287.7,294.2
XS GIS Cut Line= 2
     2339993.186      403292.438     2339729.615      402880.032
#Sta/Elev= 30
       0   600.2    11.9   600.2    31.8  598.98    43.8  592.74   45.41592.3013
    47.8  591.65    51.7  591.47    67.6  591.41   119.4   592.4   167.1  589.71
   214.9  587.94  225.62588.0275   238.8   588.3   258.6  587.83   266.6  586.38
   278.5  586.14   286.5  584.99   302.4  583.68   306.4  584.76   310.4  588.78
   318.3  599.58   322.3  603.97   326.3  607.61   342.2  617.21   358.1  625.06
   405.9  651.54   421.8  658.72   449.6  669.64   469.5  675.25   489.4  679.15
#Mann= 5 ,-1 , 0
       0    .016       0   45.41     .06       0  225.62     .12       0
   286.5    .045       0   306.4     .12       0
Bank Sta=286.5,306.4
XS Rating Curve= 0 ,0
Exp/Cntr=0.3,0.1

Type RM Length L Ch R = 1 ,3512.4  ,272.1,278.5,285.5
XS GIS Cut Line= 3
     2340164.598      403247.086     2340094.986      402930.666
     2340054.046      402777.239
#Sta/Elev= 30
       0  607.41      20  602.53      28  595.84   29.93595.7194      52  595.55
      56  594.33      64  590.36   66.29589.7875     104   586.6     116  586.15
     156  585.35     184  585.56     212  584.86  248.41 585.439     272   585.7
     300  586.96     320  582.53   331.9  581.68   335.9  581.77   339.9  582.55
   343.8  584.66   351.8  591.68   355.8  594.18   363.7  597.72   375.6  600.97
   387.5  602.26   399.4  604.46   435.1  614.41     451  620.06   482.8  624.36
#Mann= 6 ,-1 , 0
       0     .06       0   29.93    .016       0   66.29     .06       0
  248.41     .12       0     320    .045       0   339.9     .12       0
Bank Sta=320,339.9
XS Rating Curve= 0 ,0
Exp/Cntr=0.3,0.1

Type RM Length L Ch R = 1 ,3233.9  ,331.7,327.5,322.8
XS GIS Cut Line= 3
     2340378.867      403204.444      2340349.57      403088.044
     2340369.102      402718.115
#Sta/Elev= 30
       0  610.71      31  600.81   46.81594.6289    50.3  592.59    54.2  591.28
    73.6  591.14    77.4  590.82   83.36 588.892      89  586.74    92.9  586.11
     132  583.32   147.9  583.69   175.8   582.8  255.11582.4031   315.2   583.7
   327.2  582.06   335.1   579.1   343.1   578.3   347.1  578.44   351.1  579.46
     355  581.17     359  584.29     363  589.89     375  612.14   378.9  616.97
   386.9  623.37   402.8  634.75   438.7  651.46   458.6  659.22   490.5  669.37
#Mann= 6 ,-1 , 0
       0     .12       0   46.81    .016       0   83.36     .06       0
  255.11     .12       0   335.1    .045       0   351.1     .12       0
Bank Sta=335.1,351.1
XS Rating Curve= 0 ,0
Exp/Cntr=0.3,0.1

Type RM Length L Ch R = 1 ,2906.4  ,323.1,311.9,300.2
XS GIS Cut Line= 3
     2340698.409      403123.541     2340668.333      402953.111
     2340621.464      402640.501
#Sta/Elev= 30
       0  615.58    19.7  613.01    35.4  607.69    47.2  605.63   60.58601.7353
    66.9  599.51    78.7  590.73    82.6  589.37   106.2  588.22   110.1  587.11
  122.86580.9336   129.8  579.58   157.3  577.74   165.2  575.86   169.1  575.52
  179.12576.1239   188.9  579.39   196.8  580.44   248.1  579.22   263.9  579.76
   283.7  578.81   303.5  579.36   307.4  580.05   331.1  592.13   358.8  603.58
   394.3  621.53   414.1  630.76   433.8  637.21   461.5  641.21   489.2  647.53
#Mann= 5 ,-1 , 0
       0     .12       0   60.58    .016       0  122.86     .12       0
   165.2    .045       0  179.12     .12       0
#XS Ineff= 2 , 0
                          262.13          580.54
Permanent Ineff=
       F       F
Bank Sta=165.2,179.12
XS Rating Curve= 0 ,0
Exp/Cntr=0.3,0.1

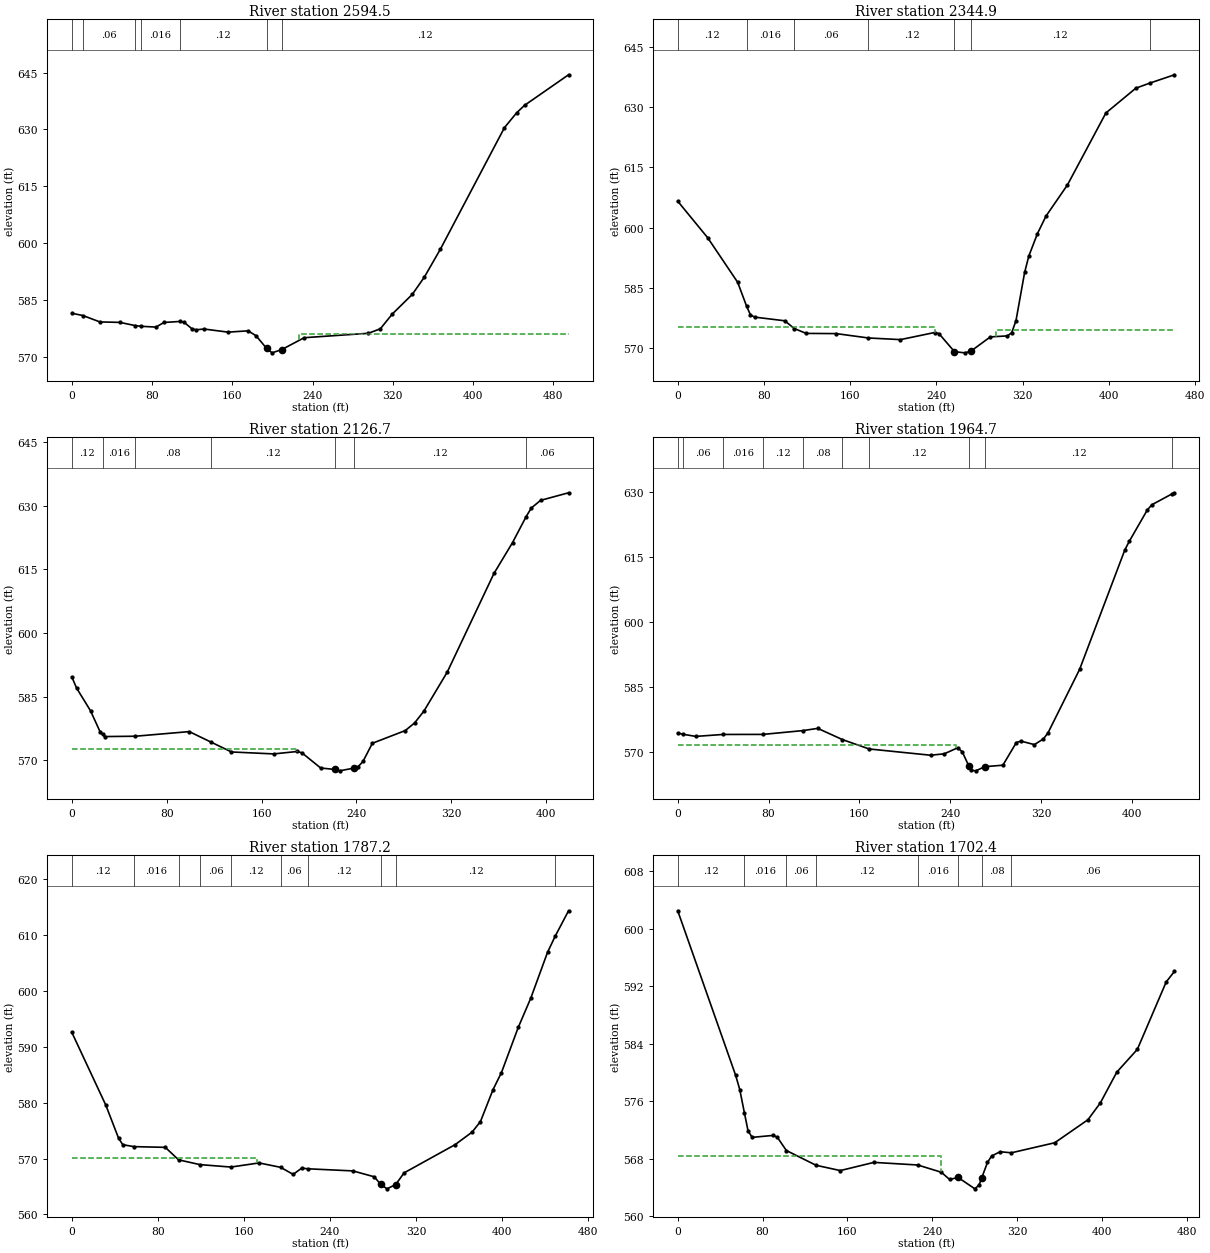
Type RM Length L Ch R = 1 ,2594.5  ,249.8,249.6,249.4
XS GIS Cut Line= 2
     2341062.181       402962.25     2340755.523      402573.286
#Sta/Elev= 30
       0  581.55   11.02 580.947      28  579.26    47.9  579.14   62.91 578.312
   68.74578.1148    83.9   577.9    91.9  579.12  107.44579.3773   111.8  579.19
   119.8  577.45   123.8  577.18   131.8  577.39   155.8  576.57   175.8  576.91
   183.7  575.62   194.3  572.26   199.7  571.11   209.3  571.97   231.7   575.1
   295.6  576.26   307.6  577.44   319.6  581.36   339.5  586.52   351.5  591.07
   367.5  598.44   431.4  630.49   443.4  634.35   451.4  636.36   495.3  644.42
#Mann= 7 ,-1 , 0
       0     .12       0   11.02     .06       0   62.91     .12       0
   68.74    .016       0  107.44     .12       0   194.3    .045       0
   209.3     .12       0
#XS Ineff= 2 , 0
                          226.52          575.95
Permanent Ineff=
       F       F
Bank Sta=194.3,209.3
XS Rating Curve= 0 ,0
Exp/Cntr=0.3,0.1

Type RM Length L Ch R = 1 ,2344.9  ,212.2,218.2,224.5
XS GIS Cut Line= 2
     2341261.029      402817.074     2340972.456      402457.824
#Sta/Elev= 30
       0  606.58    27.8  597.46    55.6  586.35   63.97580.3261    67.5  578.19
    71.5  577.65    99.3  576.74  108.12574.7991   119.2  573.59     147  573.54
  176.94 572.449   206.6  572.04   238.3  573.81   242.3  573.55   256.7  569.04
   266.2  568.74   271.7  569.11     290  572.72   305.9  572.97   309.8  573.76
   313.8  576.78   321.8   588.8   325.7   592.9   333.7  598.49   341.6  602.85
   361.5  610.63   397.2   628.6     425  634.79  437.88636.0471   460.8  638.13
#Mann= 7 ,-1 , 0
       0     .12       0   63.97    .016       0  108.12     .06       0
  176.94     .12       0   256.7    .045       0   271.7     .12       0
  437.88     .06       0
#XS Ineff= 2 , 0
          238.39  575.14  295.67          574.32
Permanent Ineff=
       F       F
Bank Sta=256.7,271.7
XS Rating Curve= 0 ,0
Exp/Cntr=0.3,0.1

Type RM Length L Ch R = 1 ,2126.7  ,165.5,161.9,157.3
XS GIS Cut Line= 3
      2341364.87      402715.945     2341256.797      402460.737
     2341173.464      402346.154
#Sta/Elev= 30
       0  589.65       4  587.03    15.8  581.65    23.8  576.74   25.92576.1149
    27.7  575.59   53.49575.6685      99  576.76  117.15 574.311   134.6  571.96
   170.2   571.5     190  572.07     194  571.76   209.8  568.18   221.7  567.84
   225.7  567.51   237.6  568.14   241.5  568.52   245.5  569.73   253.4  574.01
   281.1     577     289   578.8   296.8  581.57   316.5  590.77   355.9  614.04
   371.6  621.33  382.99 627.415   387.4  629.47   395.2  631.27   418.8  633.06
#Mann= 7 ,-1 , 0
       0     .12       0   25.92    .016       0   53.49     .08       0
  117.15     .12       0   221.7    .045       0   237.6     .12       0
  382.99     .06       0
#XS Ineff= 2 , 0
          189.89  572.57
Permanent Ineff=
       F       F
Bank Sta=221.7,237.6
XS Rating Curve= 0 ,0
Exp/Cntr=0.3,0.1

Type RM Length L Ch R = 1 ,1964.7  ,178.2,177.5,176
XS GIS Cut Line= 2
     2341554.974       402637.82     2341312.787      402273.237
#Sta/Elev= 30
       0  574.42    4.95574.1425    15.9  573.66      40 574.109   75.05574.1196
   110.1574.9918   123.4  575.51  145.16572.9201  168.69570.7625   222.8  569.32
   234.8  569.64   246.7  571.03   250.7  570.11   256.7566.7369   258.6  565.86
   262.6  565.72   270.6  566.68   286.5  567.02   298.4  572.25   302.4  572.57
   314.3  571.77   322.3   573.1   326.3  574.49   354.1   589.1   393.9  616.61
   397.9  618.65   413.8  625.88   417.8  627.07  435.84629.6161   437.7  629.83
#Mann= 10 ,-1 , 0
       0     .12       0    4.95     .06       0      40    .016       0
   75.05     .12       0   110.1     .08       0  145.16     .06       0
  168.69     .12       0   256.7    .045       0   270.6     .12       0
  435.84     .06       0
#XS Ineff= 2 , 0
           245.1  571.71
Permanent Ineff=
       F       F
Bank Sta=256.7,270.6
XS Rating Curve= 0 ,0
Exp/Cntr=0.3,0.1

Type RM Length L Ch R = 1 ,1787.2  ,85.8,84.8,84.2
XS GIS Cut Line= 4
     2341744.536      402532.525      2341662.07      402464.817
     2341509.293      402257.352     2341417.279      402225.234
#Sta/Elev= 30
       0  592.59    31.6  579.56    43.5  573.62    47.4  572.47   57.93572.1268
    86.9     572   99.27569.7629  119.06568.9089  147.87568.4696   174.1  569.21
  194.08568.4221   205.8  567.16   213.7  568.28  219.53 568.159   261.3  567.78
   281.1  566.73  287.07565.4025     293  564.57   301.1  565.34   308.9  567.43
   356.4  572.49   372.2  574.74   379.9  576.62   391.6  582.34   399.4  585.38
     415  593.46   426.7  598.72   442.3  606.94  449.44609.8328   461.8  614.36
#Mann= 10 ,-1 , 0
       0     .12       0   57.93    .016       0   99.27     .12       0
  119.06     .06       0  147.87     .12       0  194.08     .06       0
  219.53     .12       0  287.07    .045       0   301.1     .12       0
  449.44     .06       0
#XS Ineff= 2 , 0
          172.34  570.03
Permanent Ineff=
       F       F
Bank Sta=287.07,301.1
XS Rating Curve= 0 ,0
Exp/Cntr=0.3,0.1

Type RM Length L Ch R = 1 ,1702.4  ,56.2,57.1,56
XS GIS Cut Line= 4
     2341806.168      402490.859     2341750.612      402436.171
     2341572.661      402207.872     2341473.702      402187.907
#Sta/Elev= 30
       0  602.52    54.6  579.64    58.5  577.65   62.87574.4165    66.3  571.91
    70.2     571    89.8  571.27    93.8  571.04  102.44569.1714  130.46567.1168
   153.3  566.38     185  567.52  226.36567.1561   248.5  566.15   256.4  565.14
   264.3  565.43   280.2  563.84   284.2  564.39  286.53565.3154   292.1  567.52
     296  568.41     304     569  314.65568.8538   355.5  570.25   386.8  573.45
   398.5  575.79     414  580.07   433.4  583.24   460.6  592.62   468.4  594.09
#Mann= 8 ,-1 , 0
       0     .12       0   62.87    .016       0  102.44     .06       0
  130.46     .12       0  226.36    .016       0   264.3    .045       0
  286.53     .08       0  314.65     .06       0
#XS Ineff= 2 , 0
          248.71  568.36
Permanent Ineff=
       F       F
Bank Sta=264.3,286.53
XS Rating Curve= 0 ,0
Exp/Cntr=0.3,0.1

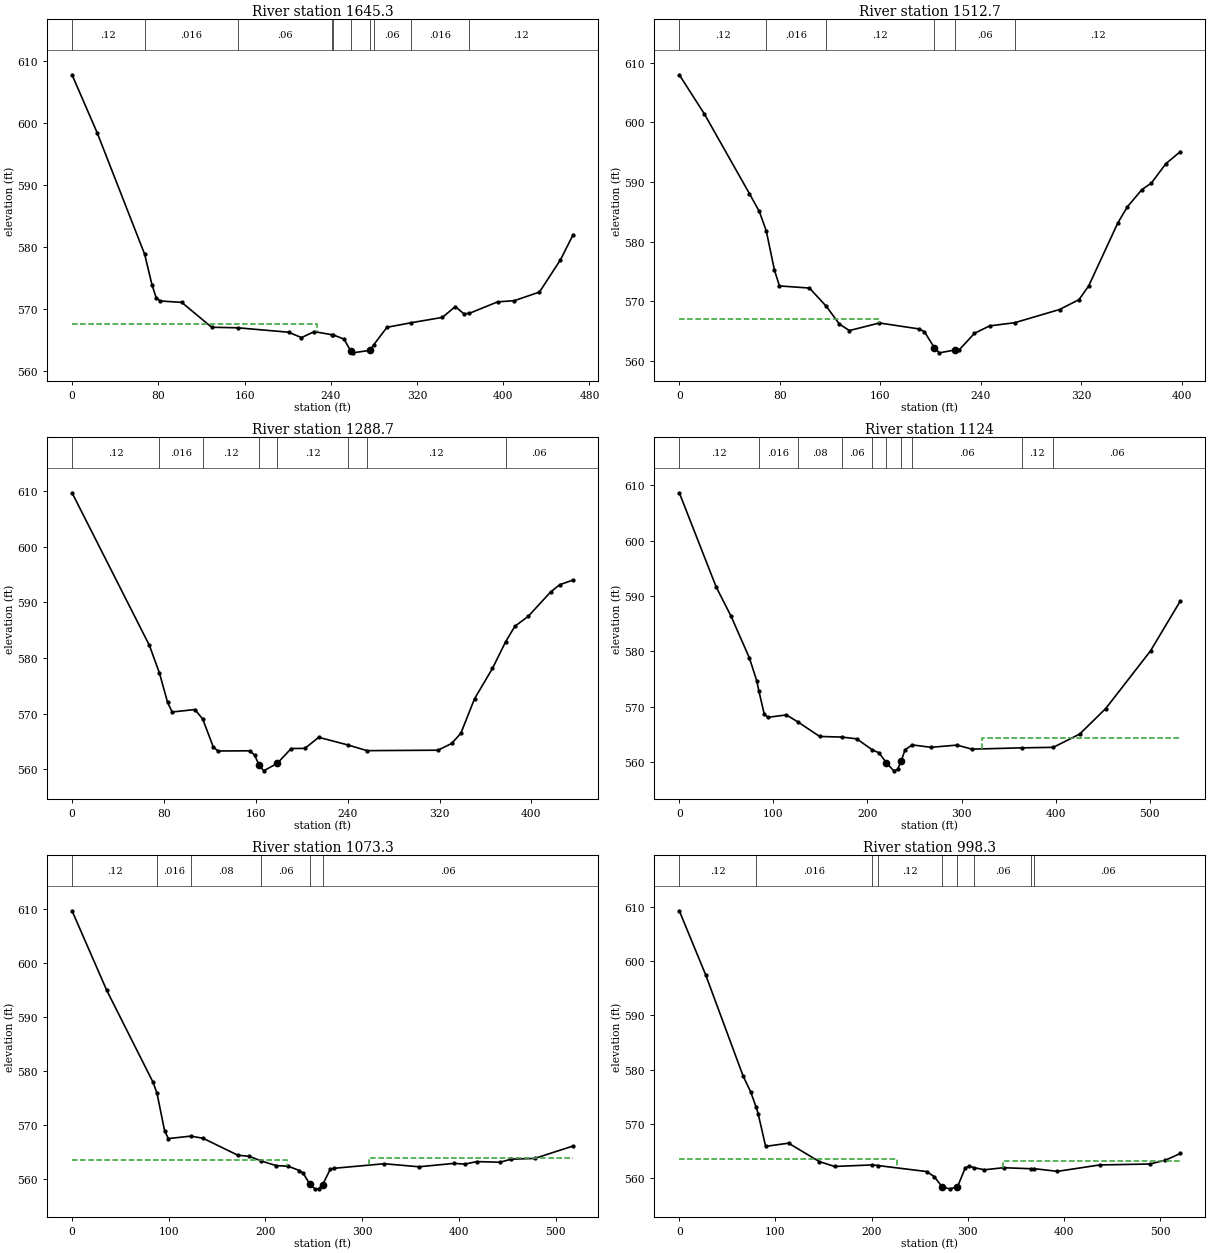
Type RM Length L Ch R = 1 ,1645.3  ,130,132.6,135.4
XS GIS Cut Line= 4
     2341850.439      402461.345     2341794.883      402406.657
     2341616.932      402178.359     2341636.029      402082.872
#Sta/Elev= 30
       0  607.81    23.4  598.42   67.37 578.847    74.1  573.96      78  571.86
    81.9  571.31   101.8  571.08   129.5  567.07     154566.9765   200.9  566.27
   212.8   565.4   224.7  566.36  241.06565.8644  242.24565.8526   252.4  565.14
  258.32563.2936   260.4  562.94   276.2  563.34  279.69564.1951   292.1  567.06
  314.11567.7831   343.6  568.66   355.5  570.41   363.4  569.25  368.54569.3117
   394.7  571.16   410.3  571.36   433.6  572.75   453.1  577.96   464.8     582
#Mann= 10 ,-1 , 0
       0     .12       0   67.37    .016       0     154     .06       0
  241.06    .016       0  242.24     .12       0  258.32    .045       0
   276.2     .12       0  279.69     .06       0  314.11    .016       0
  368.54     .12       0
#XS Ineff= 2 , 0
          227.04  567.52
Permanent Ineff=
       F       F
Bank Sta=258.32,276.2
XS Rating Curve= 0 ,0
Exp/Cntr=0.3,0.1

Type RM Length L Ch R = 1 ,1512.7  ,216.3,223.9,231.3
XS GIS Cut Line= 3
     2341911.202      402415.338     2341750.612      402154.053
     2341744.536      402062.039
#Sta/Elev= 30
       0  607.99    19.9  601.44    55.8  588.06    63.7  585.05   69.21581.8172
    75.7  575.26    79.7  572.56   103.6   572.2  116.92569.1624   127.5  566.15
   135.4  565.07   159.3  566.34   191.2  565.33   195.2  564.86   203.1  562.17
   207.1  561.33   219.1   561.8     223  561.87     235  564.61     247  565.85
  267.01566.3845   302.7   568.6   318.2  570.26   325.9  572.55     349  583.08
   356.6   585.8   368.2  588.71   375.8  589.81   387.4  593.08   398.9   595.1
#Mann= 6 ,-1 , 0
       0     .12       0   69.21    .016       0  116.92     .12       0
   203.1    .045       0   219.1     .06       0  267.01     .12       0
#XS Ineff= 2 , 0
          159.34  567.09
Permanent Ineff=
       F       F
Bank Sta=203.1,219.1
XS Rating Curve= 0 ,0
Exp/Cntr=0.3,0.1

Type RM Length L Ch R = 1 ,1288.7  ,167.4,164.7,161.8
XS GIS Cut Line= 4
     2342044.015      402352.838      2342005.82      402248.671
     2341954.605      402018.636     2341889.501      401957.004
#Sta/Elev= 30
       0  609.72    67.4  582.27   76.11577.3132    83.2  572.04    87.2  570.31
     107  570.75  113.79569.0425   122.9  564.07   126.9   563.3   154.9  563.33
   158.9  562.57   162.9  560.77   166.9  559.73   178.8  561.09   190.8  563.74
   202.8  563.77   214.8  565.76  240.52564.3652  256.82  563.36   318.6  563.44
   330.6  564.65   338.6   566.5   350.5   572.7   366.1  578.15  377.54582.9327
   385.6  585.72   397.3  587.52   416.8   591.9   424.6  593.19   436.3  594.03
#Mann= 8 ,-1 , 0
       0     .12       0   76.11    .016       0  113.79     .12       0
   162.9    .045       0   178.8     .12       0  240.52     .06       0
  256.82     .12       0  377.54     .06       0
Bank Sta=162.9,178.8
XS Rating Curve= 0 ,0
Exp/Cntr=0.3,0.1

Type RM Length L Ch R = 1 ,1124    ,42.8,50.7,58.2
XS GIS Cut Line= 4
      2342153.39      402344.157     2342154.258      402171.414
     2342073.529      401931.831     2341969.037      401908.654
#Sta/Elev= 30
       0  608.67    39.3  591.62      55  586.38    74.6   578.8    82.4  574.66
   84.61572.8533    90.3  568.68    94.2  568.11   113.8  568.54  126.36567.2488
   149.2  564.65  172.85564.5391   188.6  564.22  205.35562.2062   212.2  561.71
   220.2  559.88     228  558.44     232   558.7     236  560.26   239.9  562.24
  247.55563.1238   267.6  562.69   295.2  563.09     311  562.36  363.76562.5935
   397.5562.6854   425.6  565.08   453.3   569.7   500.9  580.12   532.6  589.13
#Mann= 10 ,-1 , 0
       0     .12       0   84.61    .016       0  126.36     .08       0
  172.85     .06       0  205.35     .12       0   220.2    .045       0
     236     .12       0  247.55     .06       0  363.76     .12       0
   397.5     .06       0
#XS Ineff= 2 , 0
                          321.98          564.29
Permanent Ineff=
       F       F
Bank Sta=220.2,236
XS Rating Curve= 0 ,0
Exp/Cntr=0.3,0.1

Type RM Length L Ch R = 1 ,1073.3  ,75.2,75,75.3
XS GIS Cut Line= 2
     2342182.904       402351.97      2342183.36      401833.827
#Sta/Elev= 30
       0  609.58    35.9  594.86    83.7  577.89   87.84575.8389    95.7  568.91
    99.6  567.45  122.82567.9095   135.5  567.51   171.4  564.38   183.3  564.17
  195.69563.3088   211.2  562.45   223.2  562.35   235.2  561.55   239.1  561.04
   245.8  559.05   251.1  558.16   255.1  558.18   259.1  558.91     267  561.78
     271  561.96   322.8   562.8   358.7  562.24   394.6  562.86   406.5  562.74
   418.5   563.2   442.4  563.08   454.4  563.65   478.3  563.78   518.1  566.08
#Mann= 6 ,-1 , 0
       0     .12       0   87.84    .016       0  122.82     .08       0
  195.69     .06       0   245.8    .045       0   259.1     .06       0
#XS Ineff= 2 , 0
          222.29  563.48  307.12          563.89
Permanent Ineff=
       F       F
Bank Sta=245.8,259.1
XS Rating Curve= 0 ,0
Exp/Cntr=0.3,0.1

Type RM Length L Ch R = 1 ,998.3   ,137.3,136,158.4
XS GIS Cut Line= 3
     2342233.425      402352.838     2342253.552      402257.353
     2342254.193      401833.827
#Sta/Elev= 30
       0  609.23    27.3  597.49    66.4  578.79    74.2  575.89   79.92573.0707
      82  571.86    89.8  565.85   113.6  566.44   145.5  563.06   161.5  562.15
  200.92562.4345  206.34562.3253   257.4  561.21   265.4  560.24   273.5  558.34
   281.4  558.03   288.5  558.35   289.4  558.44   297.4  561.89   301.4  562.22
  306.92561.9136   317.3  561.54   337.3  561.92  365.87561.7314  369.38561.7398
   393.2  561.25   437.2  562.43   489.2   562.6   505.1  563.27   521.1  564.54
#Mann= 9 ,-1 , 0
       0     .12       0   79.92    .016       0  200.92     .06       0
  206.34     .12       0   273.5    .045       0   288.5     .12       0
  306.92     .06       0  365.87     .08       0  369.38     .06       0
#XS Ineff= 2 , 0
          226.63  563.48  336.84          563.07
Permanent Ineff=
       F       F
Bank Sta=273.5,288.5
XS Rating Curve= 0 ,0
Exp/Cntr=0.3,0.1

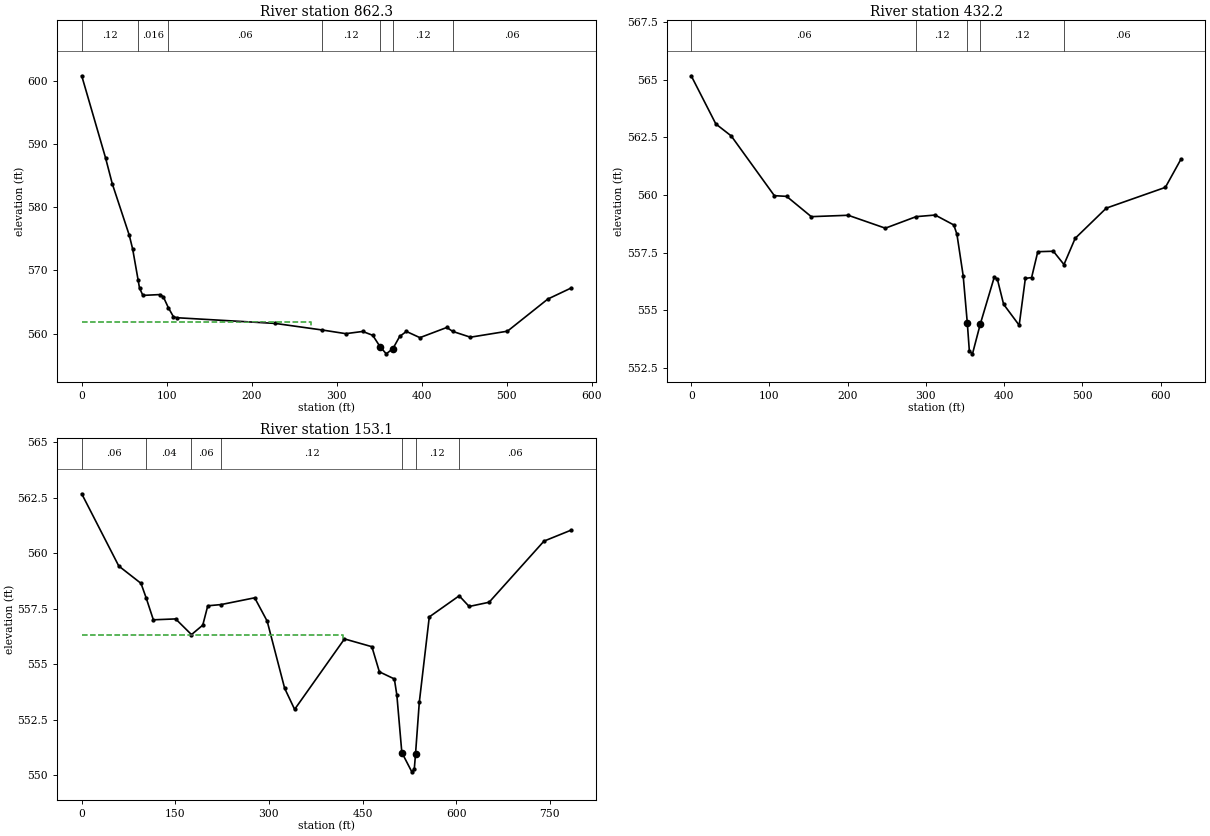
Type RM Length L Ch R = 1 ,862.3   ,428.5,430.1,404.7
XS GIS Cut Line= 3
     2342303.564      402364.122     2342401.654      402199.192
     2342357.057      401817.508
#Sta/Elev= 30
       0  600.75      28  587.79      36  583.66      56  575.52      60  573.32
   66.41568.4262      68  567.19      72  566.03      92  566.16      96  565.81
  101.89564.0952   107.9  562.66   111.9   562.5   227.6   561.6  282.62560.5662
   310.7  559.98   330.6  560.33   342.4  559.72   351.1  557.91   358.3  556.79
   366.1   557.6   374.1  559.54     382  560.33   397.9  559.35   429.6  560.96
  436.46560.3373   457.3  559.42   500.9  560.37   548.4  565.45   576.2  567.22
#Mann= 7 ,-1 , 0
       0     .12       0   66.41    .016       0  101.89     .06       0
  282.62     .12       0   351.1    .045       0   366.1     .12       0
  436.46     .06       0
#XS Ineff= 2 , 0
          269.35  561.76
Permanent Ineff=
       F       F
Bank Sta=351.1,366.1
XS Rating Curve= 0 ,0
Exp/Cntr=0.3,0.1

Type RM Length L Ch R = 1 ,432.2   ,277.6,279.1,279.6
XS GIS Cut Line= 3
     2342651.654      402338.081     2342728.043      402127.143
     2342699.505      401726.362
#Sta/Elev= 30
       0  565.17    31.5  563.08    51.2  562.56   106.3  559.97     122  559.94
   153.5  559.06   200.7  559.12   248.2  558.56  287.57559.0603   311.9  559.13
   335.7   558.7   339.7   558.3   347.7   556.5  352.99 554.448   355.6  553.23
   359.6  553.11  369.51554.3928   387.4  556.43   391.4  556.35   399.4  555.26
   419.3  554.35   427.2  556.38   435.2  556.42   443.1  557.54     463  557.56
  476.57556.9838   490.9  558.12   530.7  559.43   606.2  560.33   626.1  561.55
#Mann= 5 ,-1 , 0
       0     .06       0  287.57     .12       0  352.99    .045       0
  369.51     .12       0  476.57     .06       0
Bank Sta=352.99,369.51
XS Rating Curve= 0 ,0
Exp/Cntr=0.3,0.1

Type RM Length L Ch R = 1 ,153.1   ,151.3,153.1,154.7
XS GIS Cut Line= 3
     2342791.411      402359.782     2342979.779      402161.865
     2342957.318      401650.841
#Sta/Elev= 30
       0  562.67    59.4  559.42      95  558.64  103.31557.9827   114.8     557
   150.5  557.04  175.91556.3344     194  556.76     202  557.63   223.5557.6861
   277.2  557.99   297.2  556.94   325.2  553.92   341.2  552.97   421.1  556.14
     465  555.79     477  554.66     501  554.34     505  553.62     513  551.03
     529  550.16     533  550.29  534.96550.9711     541  553.29     557  557.13
  604.91558.0798   620.9   557.6   652.9  557.79   740.8  560.54   784.8  561.04
#Mann= 7 ,-1 , 0
       0     .06       0  103.31     .04       0  175.91     .06       0
   223.5     .12       0     513    .045       0  534.96     .12       0
  604.91     .06       0
#XS Ineff= 2 , 0
           419.4  556.31
Permanent Ineff=
       F       F
Bank Sta=513,534.96
XS Rating Curve= 0 ,0
Exp/Cntr=0.3,0.1

Chan Stop Cuts=-1
Use User Specified Reach Order=0
Composite Channel Slope=5